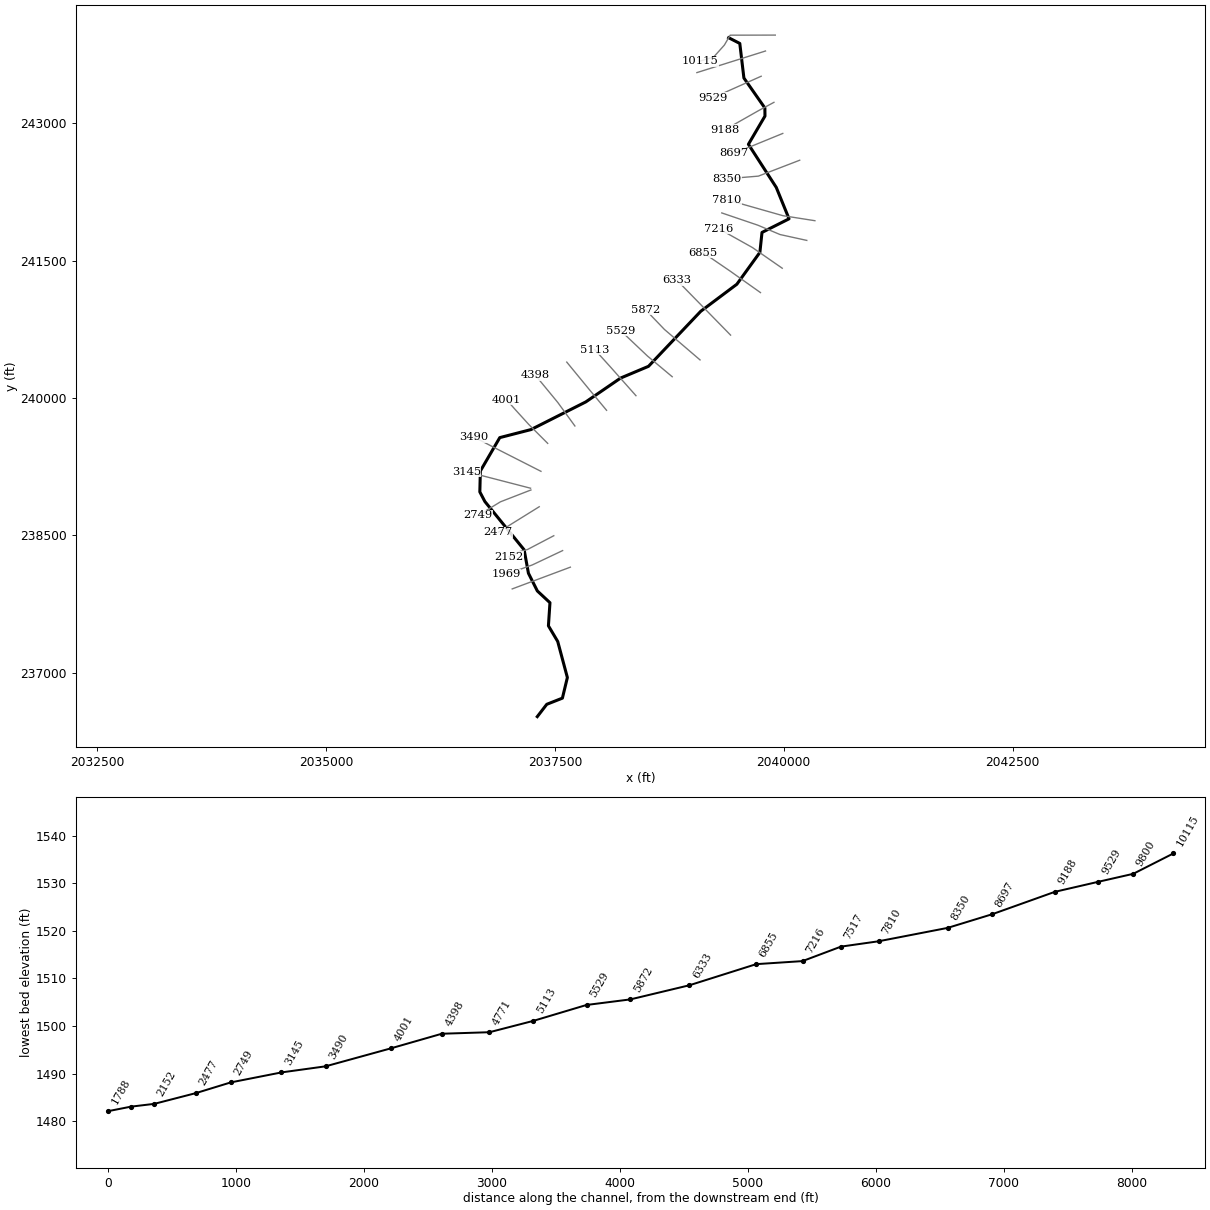
--- HNGRDCK_AE.prj (project) ---

Proj Title=HNGRDCK_AE
Current Plan=p01
Default Exp/Contr=0,0
English Units
Geom File=g01
Flow File=f01
Plan File=p01
BEGIN DESCRIPTION:
Stream Name: Hungard Creek
Flood Zone:  Detailed
Summers County, West Virginia
HEC-RAS Version: 5.0.7
Hydrology Method: Regression
Model Notes:
END DESCRIPTION:
DSS Export Rating Curves= 0
DSS Export Rating Curve Sorted= 0
DSS Export Volume Flow Curves= 0
DXF OffsetX= 0
DXF OffsetY= 0
DXF ScaleX= 0
DXF ScaleY= 0

--- HNGRDCK_AE.p01 (plan) ---

Plan Title=Floodplain
Program Version=5.07
Short Identifier=Floodplain
Geom File=g01
Flow File=f01
Subcritical Flow
K Sum by GR= 0
Std Step Tol= 0.01
Critical Tol= 0.01
Num of Std Step Trials= 20
Max Error Tol= 0.3
Flow Tol Ratio= 0.001
Split Flow NTrial= 30
Split Flow Tol= 0.02
Split Flow Ratio= 0.02
Log Output Level= 0
Friction Slope Method= 1
Unsteady Friction Slope Method= 2
Unsteady Bridges Friction Slope Method= 1
Parabolic Critical Depth
Global Vel Dist= 0 , 0 , 0
Global Log Level= 0
CheckData=True
Encroach Param=-1 ,10,10, 2
Encroach River=HNGRDCK_AE
Encroach Reach=Main
Encroach Node=10115
       1  503.93     612
Encroach Node=9800
       1   265.9     360
Encroach Node=9529
       1     153     300
Encroach Node=9188
       1    90.2     270
Encroach Node=8697
       1     280     409
Encroach Node=8350
       1     260     440
Encroach Node=7810
       1     260     465
Encroach Node=7517
       1     360     530
Encroach Node=7216
       1     284     470
Encroach Node=6855
       1   240.4   432.1
Encroach Node=6333
       1     375   504.2
Encroach Node=5872
       1     270   440.6
Encroach Node=5529
       1     205     350
Encroach Node=5113
       1   223.7     330
Encroach Node=4771
       1     177     265
Encroach Node=4398
       1     152     250
Encroach Node=4001
       1   202.4     300
Encroach Node=3490
       1     480     630
Encroach Node=3145
       1     450     608
Encroach Node=2749
       1     400     525
Encroach Node=2477
       1     350     480
Encroach Node=2152
       1  305.72  464.61
Encroach Node=1969
       1     389     508
Encroach Node=1788
       1     360     500
Encroach Node=1559
       1  315.28     475
Encroach Node=1384
       1     364     447
Encroach Node=1281
       1     364     421
Encroach Node=1101
       1  306.78  504.33
Encroach Node=981
       1  243.38     547
Encroach Node=834
       1     590     713
Encroach Node=594
       1     607     713
Mapping Interval=1HOUR
Computation Time Step Use Courant=        0
Computation Time Step Use Time Series=    0
Computation Time Step Count To Double=0
Computation Time Step Max Doubling=0
Computation Time Step Max Halving=0
Computation Time Step Residence Courant=0
Run HTab= 0
Run UNet= 0
Run Sediment= 0
Run PostProcess= 0
Run WQNet= 0
Run RASMapper= 0
UNET Theta= 0
UNET Theta Warmup= 0
UNET ZTol= 0
UNET ZSATol= 0
UNET MxIter= 0
UNET Max Iter WO Improvement= 0
UNET MaxInSteps= 0
UNET DtIC= 0
UNET DtMin= 0
UNET MaxCRTS= 0
UNET WFStab= 0
UNET SFStab= 0
UNET WFX= 1
UNET SFX= 1
UNET 1D Methodology=Finite Difference
UNET DSS MLevel= 1
UNET Pardiso=0
UNET DZMax Abort= 0
UNET Use Existing IB Tables= 0
UNET Froude Reduction=False
UNET Froude Limit= 0
UNET Froude Power= 0
UNET D1 Cores= 0
UNET D2 Coriolis=0
UNET D2 Cores= 0
UNET D2 Theta= 1
UNET D2 Theta Warmup= 1
UNET D2 Z Tol= 0.01
UNET D2 Volume Tol= 0.01
UNET D2 Max Iterations= 20
UNET D2 Equation= 0
UNET D2 RampUpFraction=0.1
UNET D2 TimeSlices= 1
UNET D2 BCVolumeCheck=0
UNET D1D2 MaxIter= 0
UNET D1D2 ZTol=0.01
UNET D1D2 QTol=0.1
UNET D1D2 MinQTol=1
Write IC File= 0
Write IC File at Fixed DateTime=0
Write IC File at Sim End=0
Echo Input=False
Echo Parameters=False
Echo Output=False
Write Detailed= 0
HDF Write Warmup=0
HDF Write Time Slices=0
HDF Flush=0
HDF Face Node Velocities=0
HDF Compression= 1
HDF Chunk Size= 1
HDF Spatial Parts= 1
HDF Use Max Rows=0
HDF Fixed Rows= 1
Calibration Method= 0
Calibration Iterations= 20
Calibration Max Change=0.05
Calibration Tolerance=0.2
Calibration Maximum=1.5
Calibration Minimum=0.5
Calibration Optimization Method= 1
WQ AD Non Conservative
WQ ULTIMATE=-1
WQ Max Comp Step=1HOUR
WQ Output Interval=15MIN
WQ Output Selected Increments= 0
WQ Output face flow=0
WQ Output face velocity=0
WQ Output face area=0
WQ Output face dispersion=0
WQ Output cell volume=0
WQ Output cell surface area=0
WQ Output cell continuity=0
WQ Output cumulative cell continuity=0
WQ Output face conc=0
WQ Output face dconc_dx=0
WQ Output face courant=0
WQ Output face peclet=0
WQ Output face adv mass=0
WQ Output face disp mass=0
WQ Output cell mass=0
WQ Output cell source sink temp=0
WQ Output nsm pathways=0
WQ Output nsm derived pathways=0
WQ Output MaxMinRange=-1
WQ Daily Max Min Mean=-1
WQ Daily Range=0
WQ Daily Time=0
WQ Create Restart=0
WQ Fixed Restart=0
WQ System Summary=0
WQ Write To DSS=0
WQ Use Fixed Temperature=0
Sorting and Armoring Iterations= 10
XS Update Threshold= 0.02
Bed Roughness Predictor= 0
Hydraulics Update Threshold= 0.02
Energy Slope Method= 1
Volume Change Method= 1
Sediment Retention Method= 0
XS Weighting Method= 0
Number of US Weighted Cross Sections= 1
Number of DS Weighted Cross Sections= 1
Upstream XS Weight=0
Main XS Weight=1
Downstream XS Weight=0
Number of DS XS's Weighted with US Boundary= 1
Upstream Boundary Weight= 1
Weight of XSs Associated with US Boundary= 0
Number of US XS's Weighted with DS Boundary= 1
Downstream Boundary Weight= 0.5
Weight of XSs Associated with DS Boundary= 0.5
Percentile Method= 0
Sediment Output Level= 3
Mass or Volume Output= 0
Output Increment Type= 1
Profile and TS Output Increment= 1
XS Output Flag= 0
XS Output Increment= 10
Write Gradation File= 0
Read Gradation Hotstart= 0
Write HDF5 File= 1
Write Binary Output= 1
Write DSS Sediment File= 0
SV Curve= 0
Specific Gage Flag= 0

--- HNGRDCK_AE.f01 (steady flow) ---

Flow Title=Flows
Program Version=5.07
Number of Profiles= 7
Profile Names=01pct,FW,10pct,04pct,02pct,0_2pct,01plus
River Rch & RM=HNGRDCK_AE,Main            ,10115
    3054    3054    1722    2219    2624    4134    4517
Boundary for River Rch & Prof#=HNGRDCK_AE,Main            , 1
Up Type= 0
Dn Type= 3
Dn Slope=0.00366
Boundary for River Rch & Prof#=HNGRDCK_AE,Main            , 2
Up Type= 0
Dn Type= 3
Dn Slope=0.00366
Boundary for River Rch & Prof#=HNGRDCK_AE,Main            , 3
Up Type= 0
Dn Type= 3
Dn Slope=0.00366
Boundary for River Rch & Prof#=HNGRDCK_AE,Main            , 4
Up Type= 0
Dn Type= 3
Dn Slope=0.00366
Boundary for River Rch & Prof#=HNGRDCK_AE,Main            , 5
Up Type= 0
Dn Type= 3
Dn Slope=0.00366
Boundary for River Rch & Prof#=HNGRDCK_AE,Main            , 6
Up Type= 0
Dn Type= 3
Dn Slope=0.00366
DSS Import GetInterval= 0
DSS Import GetPeak= 0
DSS Import FillOption= 0

--- HNGRDCK_AE.g01 (geometry) ---

Geom Title=Geometry
Program Version=5.07

River Reach=HNGRDCK_AE      ,Main
Reach XY= 30
2039398.69934794243936.620250806     2039519.993243874.253999993
     2039564.869243496.6270000192039793.93999998243169.194999993
2039795.04900001243080.5039999932039614.17800003242772.258000001
     2039918.579242301.0220000152040058.18800002      241958.022
2039762.61499998241809.1500000212039739.56300001241591.422000036
     2039487.875241243.1780000182039092.95200001240947.246000022
     2038522.164240346.0429999982038217.33399999240217.763999999
2037837.70200004      239957.5882037238.74300003239655.070999995
     2036897.164      239566.9632036684.92400001239201.945999995
2036679.28200005238973.6470000152036734.40300001238868.612000018
2037163.54599999238341.106000006       2037210.3      238085.169
     2037307.667 237891.54900001     2037445.601237763.143000007
2037428.81000003237510.3359999952037530.32300003237339.532000005
2037635.87900002236945.4790000172037581.54896626236720.180229545
2037410.66875398236652.8038934622037307.16217375236518.290477991

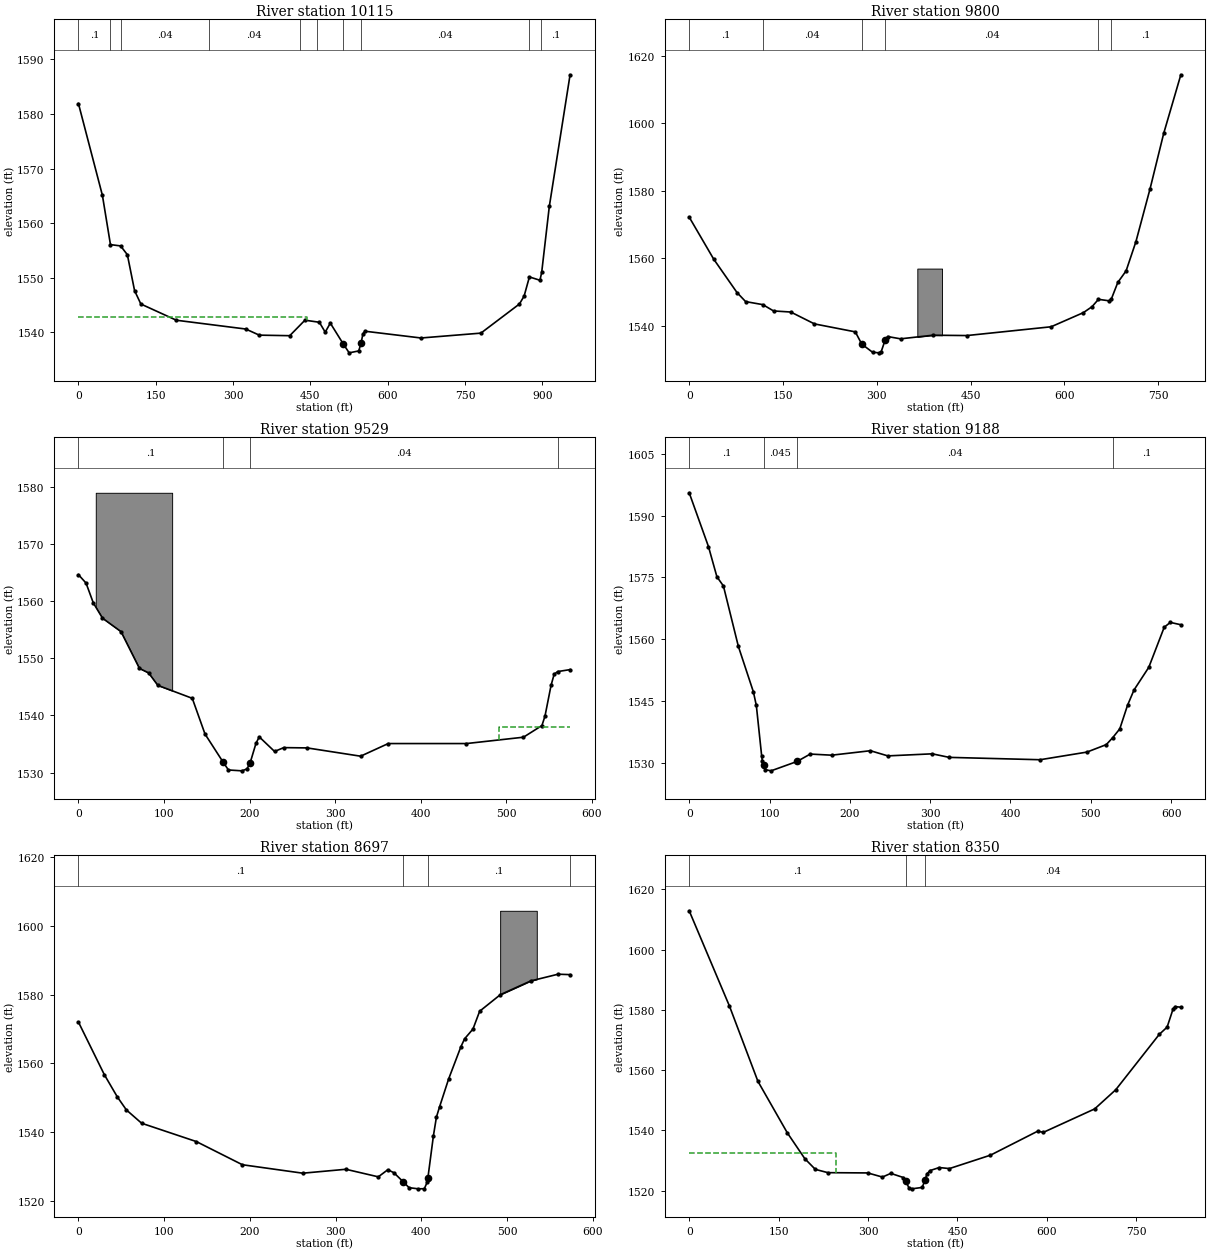
Type RM Length L Ch R = 1 ,10115   ,325.3,314.7,214.8
XS GIS Cut Line= 6
2039908.00917245243965.5950568542039415.02198315 243964.61658924
2039412.59741889243961.1458892972039350.98622531243855.760894224
2039234.22641762243725.5804189892039081.26978616243680.259935588
#Sta/Elev= 30
       0 1581.91    46.5  1565.1    62.1 1556.08    81.8 1555.84    94.9 1554.23
   108.9 1547.65   121.1  1545.2     190 1542.23   324.6 1540.62   350.8  1539.5
   409.9  1539.4   439.4 1542.24   467.3 1541.86   478.7 1540.05   488.6  1541.7
 513.9341537.855   525.2 1536.26   543.7 1536.61 548.1021537.971   551.9 1539.75
   555.7 1540.22   664.5 1538.98   780.7 1539.87   855.4  1545.2   864.5 1546.64
   874.8 1550.16   895.3 1549.55   898.7 1551.04   913.4 1563.06   953.7 1587.18
#Mann= 10 ,-1 , 0
       0      .1       0  62.083    .013       0  81.768     .04       0
 252.372     .04       0 429.537    .013       0 462.345     .04       0
 513.934    .045       0 548.102     .04       0 873.848    .013       0
 897.605      .1       0
#XS Ineff= 2 , 0
          443.94 1542.89
Permanent Ineff=
       F       F
Bank Sta=513.934,548.102
XS Rating Curve= 0 ,0
Exp/Cntr(USF)=0,0
Exp/Cntr=0.3,0.1

Type RM Length L Ch R = 1 ,9800    ,270.1,270.9,283.9
Node Name=C
XS GIS Cut Line= 2
2039800.73246009243791.6727906092039051.05613055243555.628606243
#Sta/Elev= 30
       0 1572.17    39.2 1559.72    76.4 1549.84    90.2 1547.15   117.7 1546.25
   134.9 1544.38   162.4 1544.06   200.3 1540.54   265.6 1538.18   275.9 1534.55
   293.1 1532.15   303.5 1531.97   306.9 1532.29   313.5 1535.88   317.2  1536.8
   337.9 1536.12   389.5 1537.19     444 1537.09   578.6 1539.69   630.2 1543.88
     644 1545.64   654.3 1547.82   671.5 1547.38   674.9 1547.91   685.3 1552.85
   698.5 1556.25   714.2 1564.91   736.9 1580.64   758.6 1596.97     786 1614.34
#Mann= 6 ,-1 , 0
       0      .1       0   117.7     .04       0   275.9    .045       0
   313.5     .04       0   654.3    .016       0   674.9      .1       0
#Block Obstruct= 1 ,-1
  364.71  404.24 1556.93
Bank Sta=275.9,313.5
XS Rating Curve= 0 ,0
Exp/Cntr(USF)=0,0
Exp/Cntr=0.3,0.1

Type RM Length L Ch R = 1 ,9529    ,339.9,341.4,346.9
XS GIS Cut Line= 2
2039753.52362322243515.9731832692039228.56135719243281.817352378
#Sta/Elev= 30
       0 1564.61     8.9 1563.14    17.4 1559.67    28.1 1557.01    49.7 1554.66
    71.3 1548.23      82 1547.44    92.8 1545.26   133.1 1542.99     148 1536.74
   169.2 1531.82   175.4 1530.46   191.2 1530.31     197 1530.65   200.6 1531.63
   207.6 1535.13   211.4 1536.25   229.3  1533.7   240.1 1534.37   267.3 1534.32
   329.9 1532.87   362.2 1535.08   453.6 1535.08   520.3 1536.19   541.9 1538.23
   545.5  1539.9   552.6 1545.28   556.2 1547.21   560.4 1547.67   574.8 1548.01
#Mann= 4 ,-1 , 0
       0      .1       0   169.2    .045       0   200.6     .04       0
   560.4    .016       0
#XS Ineff= 2 , 0
                          491.83         1537.91
Permanent Ineff=
       F       F
#Block Obstruct= 1 ,-1
   20.26  109.56 1578.93
Bank Sta=169.2,200.6
XS Rating Curve= 0 ,0
Exp/Cntr(USF)=0,0
Exp/Cntr=0.3,0.1

Type RM Length L Ch R = 1 ,9188    ,434.2,490.4,346.4
XS GIS Cut Line= 3
2039893.26178036243230.831808555 2039725.1983211243140.190841758
2039358.85774696242932.471959515
#Sta/Elev= 30
       0 1595.51      24 1582.48    34.5 1575.17    42.6 1572.95    61.2 1558.33
    79.9 1547.32    83.6 1544.01    90.2 1531.85    91.1 1530.54    92.6  1529.6
    94.8 1528.47   101.9 1528.19   134.3 1530.46   150.7 1532.25   177.4 1531.98
   225.6 1533.06   247.3 1531.81   302.6 1532.31   323.7 1531.45   436.9 1530.88
   495.2 1532.73   519.3 1534.54   527.4 1536.25   536.1 1538.36   545.7 1544.04
   553.8 1547.77   572.2 1553.25   591.4 1562.95     599 1564.13   612.1 1563.56
#Mann= 4 ,-1 , 0
       0      .1       0    92.6    .045       0   134.3     .04       0
   527.4      .1       0
Bank Sta=92.6,134.3
XS Rating Curve= 0 ,0
Exp/Cntr(USF)=0,0
Exp/Cntr=0.3,0.1

Type RM Length L Ch R = 1 ,8697    ,334.9,347.2,342.8
XS GIS Cut Line= 2
2039989.56780759242890.9281830672039458.94048113 242673.76753345
#Sta/Elev= 30
       0 1571.99    30.2 1556.69    45.3 1550.24    55.9 1546.44    73.7 1542.56
   137.5 1537.23   191.2 1530.49   261.6 1528.03   311.9 1529.17   349.7 1526.97
   360.8 1529.04   367.9 1528.16   378.5 1525.59   385.6 1523.82   396.3 1523.48
   403.4 1523.52   406.9 1525.54   407.5 1526.59     414 1538.96   417.5 1544.36
   421.1 1547.29   431.7 1555.43   445.9 1564.73   450.3 1567.11   460.1 1569.96
   467.9 1575.14     492 1579.95   527.4 1583.95   559.3 1585.91   573.3 1585.79
#Mann= 4 ,-1 , 0
       0      .1       0   378.5    .045       0   407.5      .1       0
573.3447     .03       0
#Block Obstruct= 1 ,-1
   491.8  534.52 1604.36
Bank Sta=378.5,407.5
XS Rating Curve= 0 ,0
Exp/Cntr(USF)=0,0
Exp/Cntr=0.3,0.1

Type RM Length L Ch R = 1 ,8350    ,549.1,539.7,439.8
XS GIS Cut Line= 3
2040174.62644813242598.2333944532039723.30996762242424.504874759
2039383.40634213242396.179572635
#Sta/Elev= 30
       0 1612.93    67.5 1581.31   115.3  1556.3   164.5 1539.24     194 1530.62
   211.6 1527.08   232.7 1525.99   299.5  1525.9   324.1 1524.53   338.2 1525.75
   359.2 1524.38   363.5 1523.07   368.6 1520.95   373.3 1520.62   390.9 1521.09
   395.4 1523.48     399 1525.63   404.1 1526.69   419.4 1527.69   436.6 1527.35
   505.4  1531.8   584.4 1539.74   594.3 1539.39   680.2 1547.16   715.5 1553.51
   788.5 1571.89   801.7 1574.31   811.6 1580.28   814.9 1581.12   824.7 1580.92
#Mann= 3 ,-1 , 0
       0      .1       0   363.5    .045       0   395.4     .04       0
#XS Ineff= 2 , 0
          246.76 1532.56
Permanent Ineff=
       F       F
Bank Sta=363.5,395.4
XS Rating Curve= 0 ,0
Exp/Cntr(USF)=0,0
Exp/Cntr=0.3,0.1

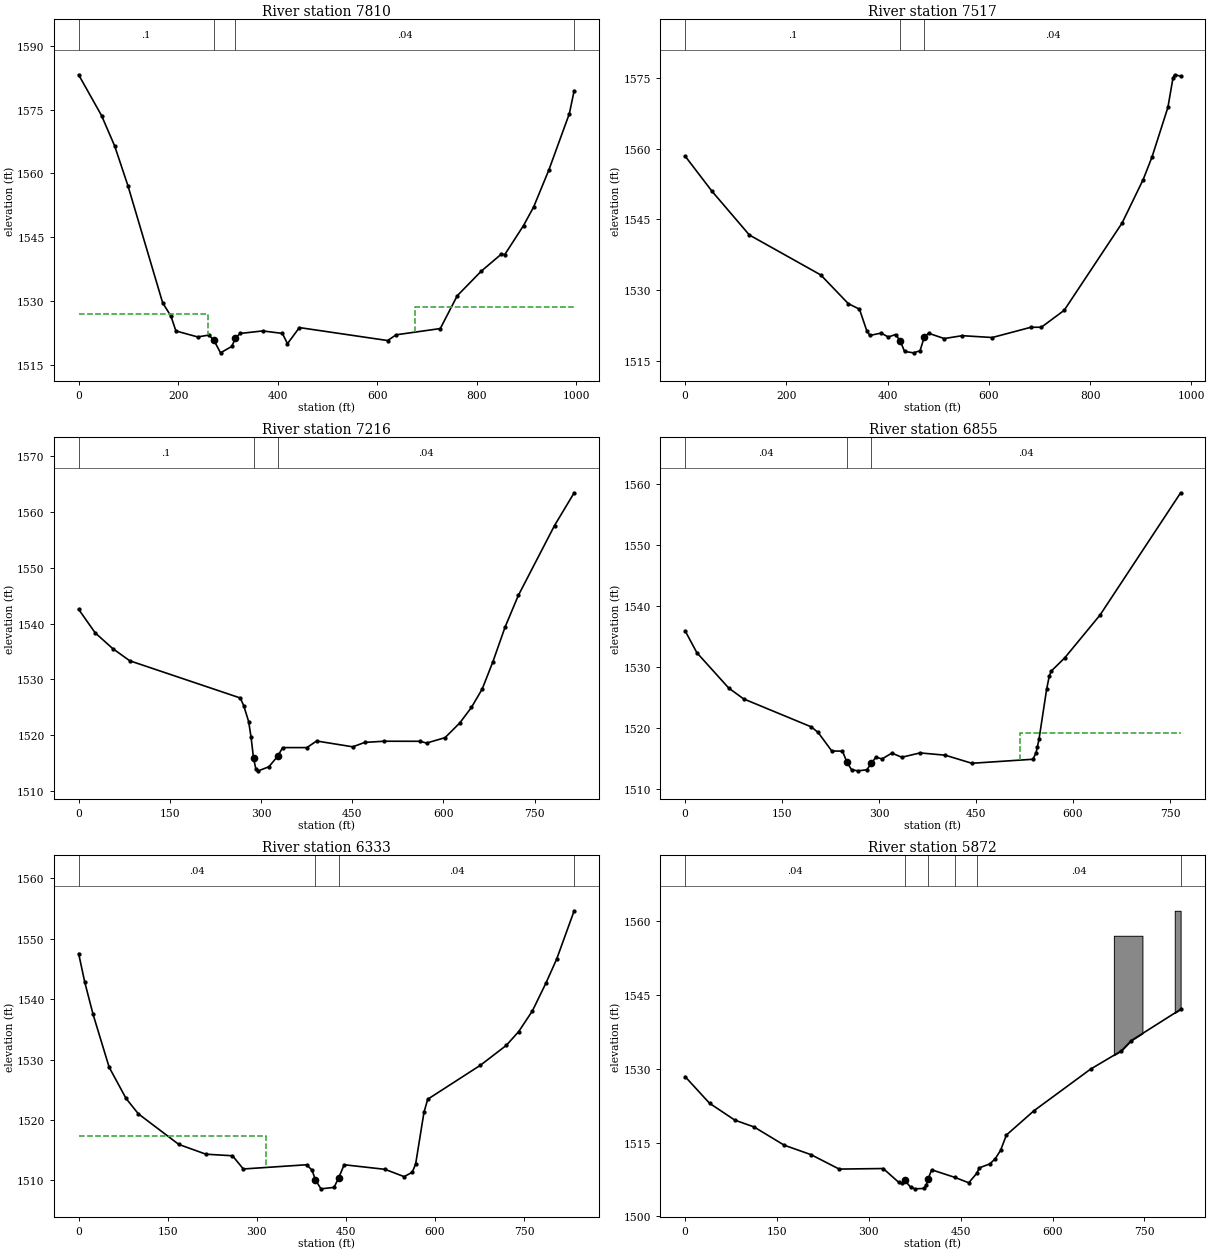
Type RM Length L Ch R = 1 ,7810    ,270.2,293.4,185.9
XS GIS Cut Line= 3
2040340.80155392241937.3096782272039991.45616106   241992.071929
2039373.96457476242167.688802168
#Sta/Elev= 30
       0  1583.2      46 1573.62    72.5 1566.43    99.1 1557.09   168.8 1529.58
   185.4 1526.46   195.4 1522.96   239.1 1521.55   261.8 1521.99   271.8 1520.75
   285.1 1517.81     308 1519.34   314.9  1521.3   324.5 1522.37   369.8 1522.96
   409.4 1522.38   419.6 1519.96   443.5 1523.75   620.9  1520.7   637.9 1522.05
   726.6 1523.52   760.7 1531.24   808.5 1536.97   849.4 1541.04   856.2 1540.92
   893.8 1547.74   914.2 1552.12   944.9 1560.86   985.9 1574.06   995.6 1579.47
#Mann= 4 ,-1 , 0
       0      .1       0   271.8    .045       0   314.9     .04       0
   995.6      .1       0
#XS Ineff= 2 , 0
             260 1526.88     675         1528.69
Permanent Ineff=
       F       F
Bank Sta=271.8,314.9
XS Rating Curve= 0 ,0
Exp/Cntr(USF)=0,0
Exp/Cntr=0.3,0.1

Type RM Length L Ch R = 1 ,7517    ,273.5,300.5,243.9
XS GIS Cut Line= 4
 2040252.0489406241722.0373820852039959.35415199241786.241400232
 2039717.6449072241888.2124878792039322.97903094242022.285584599
#Sta/Elev= 30
       0 1558.43      53 1550.98   126.9 1541.69     268 1533.21   322.3 1527.13
   344.4 1525.95   358.7 1521.42   364.9 1520.38   387.2 1520.88   401.4 1520.05
   415.6 1520.57     425 1519.21   433.4 1516.99   451.2 1516.69   464.1 1517.14
   472.6  1520.1     481 1520.84   511.8 1519.72   547.4 1520.33   606.7 1519.94
   682.9 1522.11   703.7 1522.12   748.8 1525.71   863.1 1544.22   904.7 1553.42
   922.3 1558.24   953.7 1568.78   963.7 1575.01     967 1575.67   978.8 1575.38
#Mann= 3 ,-1 , 0
       0      .1       0     425    .045       0   472.6     .04       0
Bank Sta=425,472.6
XS Rating Curve= 0 ,0
Exp/Cntr(USF)=0,0
Exp/Cntr=0.3,0.1

Type RM Length L Ch R = 1 ,7216    ,354,361.7,345
XS GIS Cut Line= 3
2039983.90274716241418.012472621  2039657.217596241644.614889612
2039292.76537534241848.557064905
#Sta/Elev= 30
       0 1542.57    27.2 1538.35    56.1 1535.53    84.1 1533.35   265.9 1526.69
   271.7 1525.28   279.7 1522.46   283.7 1519.65   287.7 1515.91   291.7 1513.92
   295.7 1513.65     313 1514.38   327.6 1516.28   335.6 1517.81   375.5 1517.81
   391.5 1518.99   450.9 1517.95   470.8 1518.74   502.7 1518.95   561.8 1518.94
   572.3 1518.62   602.8 1519.59   626.9 1522.21   646.2    1525     664 1528.32
   681.4 1533.15   701.6  1539.4   723.3 1545.04   782.9 1557.56   815.2 1563.42
#Mann= 3 , 0 , 0
       0      .1       0   287.7    .045       0   327.6     .04       0
Bank Sta=287.7,327.6
XS Rating Curve= 0 ,0
Exp/Cntr(USF)=0,0
Exp/Cntr=0.3,0.1

Type RM Length L Ch R = 1 ,6855    ,524.7,521.6,483.9
XS GIS Cut Line= 3
2039745.97020932241151.7546326552039415.50835121241385.910463547
2039117.14850217241589.852638839
#Sta/Elev= 30
       0 1535.99    18.2 1532.39    67.4  1526.6    90.4 1524.82   195.2 1520.22
   205.7 1519.31   226.9 1516.26   243.4 1516.25   250.4  1514.4   257.5 1513.18
   267.5 1513.01     281 1513.18   288.1 1514.23   295.1 1515.26   304.5 1514.96
   319.8 1515.92   335.1 1515.24   363.4 1515.95   402.2 1515.58   443.5 1514.25
   537.9 1514.91   542.7 1515.95     545 1516.99   547.5 1518.29   559.2 1526.43
   563.2 1528.54   566.3 1529.38   587.1 1531.54   641.8 1538.58   766.4 1558.63
#Mann= 3 ,-1 , 0
       0     .04       0   250.4    .045       0   288.1     .04       0
#XS Ineff= 2 , 0
                          518.31          1519.3
Permanent Ineff=
       F       F
Bank Sta=250.4,288.1
XS Rating Curve= 0 ,0
Exp/Cntr(USF)=0,0
Exp/Cntr=0.3,0.1

Type RM Length L Ch R = 1 ,6333    ,457.9,461.5,466.4
Node Name=B
XS GIS Cut Line= 2
2039419.28505816240687.219677822 2038835.7838344241283.939375901
#Sta/Elev= 30
       0 1547.56    10.3 1542.83    24.2 1537.53    51.4 1528.73    79.9 1523.55
   100.7    1521   168.7 1515.94   214.4 1514.32   259.1 1514.06   277.4 1511.87
   383.8 1512.57   393.1 1511.68   398.7 1510.09   408.1 1508.58   430.2 1508.82
   438.1 1510.43   447.2 1512.57   516.1 1511.81   548.2  1510.6   561.9 1511.33
   567.6 1512.69   581.7  1521.3     588 1523.43   676.7 1529.06   720.2 1532.34
   741.1 1534.63   764.3 1538.07   786.8 1542.62   805.1 1546.64   834.6 1554.65
#Mann= 4 ,-1 , 0
       0     .04       0   398.7    .045       0   438.1     .04       0
834.5945     .04       0
#XS Ineff= 2 , 0
          314.93 1517.41
Permanent Ineff=
       F       F
Bank Sta=398.7,438.1
XS Rating Curve= 0 ,0
Exp/Cntr(USF)=0,0
Exp/Cntr=0.3,0.1

Type RM Length L Ch R = 1 ,5872    ,340.8,342.7,346.5
XS GIS Cut Line= 3
2039085.61299914240416.0521188222038696.42334795  240749.1576718
2038490.78165453240963.296955857
#Sta/Elev= 30
       0 1528.39      40 1522.97    81.3 1519.55   112.6 1518.17     162 1514.46
   205.6 1512.55   251.6 1509.62   323.5 1509.73   348.7 1506.95   353.8 1506.75
   358.8 1507.34   368.2 1505.95   375.5 1505.61   389.8 1505.69   394.1 1506.43
   396.4 1507.51   402.7 1509.47   440.6 1507.93   463.2 1506.84   476.1 1508.73
   480.5 1509.87   497.7 1510.68   506.4 1511.71   515.1 1513.41   524.7 1516.53
   569.5 1521.44   662.1  1529.9   712.3  1533.6   728.7  1535.7   809.2 1542.04
#Mann= 6 ,-1 , 0
       0     .04       0   358.8    .045       0   396.4     .04       0
   440.6     .08       0   476.1     .04       0 809.168     .03       0
#Block Obstruct= 2 ,-1
  700.15   746.8 1556.97  799.57  809.17 1562.04
Bank Sta=358.8,396.4
XS Rating Curve= 0 ,0
Exp/Cntr(USF)=0,0
Exp/Cntr=0.3,0.1

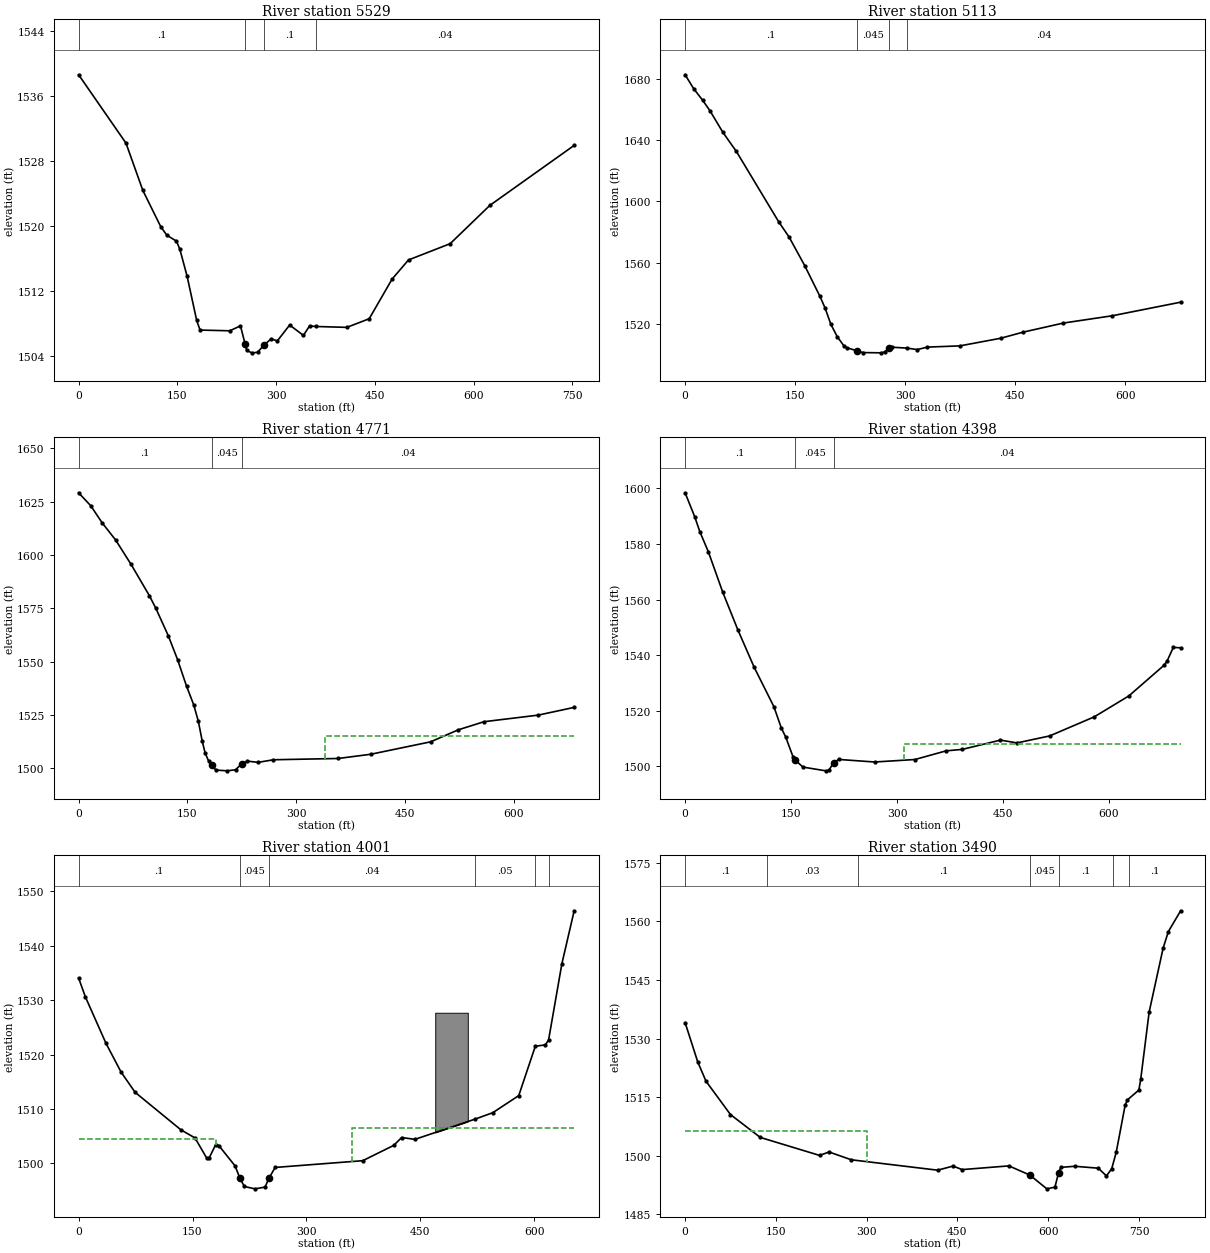
Type RM Length L Ch R = 1 ,5529    ,419.3,415.7,386.5
XS GIS Cut Line= 3
2038781.39925432240232.5041610592038511.17587206240458.540072008
2038220.55827227240733.862008653
#Sta/Elev= 30
       0 1538.62    71.9 1530.22    97.5 1524.41   124.8 1519.93   134.1 1518.89
   148.6 1518.17   153.7 1517.18   164.8 1513.84   179.3 1508.42   184.4 1507.24
   229.6 1507.15   245.8 1507.76   252.9  1505.5   255.2 1504.73   263.2 1504.44
   271.7  1504.5   281.6  1505.4   292.5 1506.17   301.7  1505.9   320.5 1507.86
   341.4 1506.58   350.7 1507.75     360 1507.68   407.3 1507.57   441.3 1508.63
   476.1 1513.51     501 1515.86   564.3 1517.86   624.6 1522.57   752.6 1529.94
#Mann= 4 ,-1 , 0
       0      .1       0   252.9    .045       0   281.6      .1       0
     360     .04       0
Bank Sta=252.9,281.6
XS Rating Curve= 0 ,0
Exp/Cntr(USF)=0,0
Exp/Cntr=0.3,0.1

Type RM Length L Ch R = 1 ,5113    ,345.1,342.6,340.8
XS GIS Cut Line= 3
2038385.41153063240025.1629495122038101.59200335 240344.67235747
2037935.03922686240528.220315233
#Sta/Elev= 30
       0 1682.68    11.8 1673.54    23.9 1666.05    33.8 1659.25    51.3 1645.23
    69.9 1632.58   127.6 1586.62   141.6 1576.79   162.9 1558.12   183.8 1537.92
   190.8  1530.3   198.6 1519.72   207.4 1511.57   216.5 1505.59   220.5 1504.42
   233.7  1502.5   242.5 1501.27   267.5  1501.1   272.1 1501.71   277.6 1503.95
     282 1504.77   302.3 1504.19   316.3 1503.23   330.2 1504.85   374.4 1505.64
   430.1 1510.64   460.3 1514.58   515.4 1520.55   581.9  1525.3   675.2 1534.18
#Mann= 4 ,-1 , 0
       0      .1       0   233.7    .045       0   277.6      .1       0
   302.3     .04       0
Bank Sta=233.7,277.6
XS Rating Curve= 0 ,0
Exp/Cntr(USF)=0,0
Exp/Cntr=0.3,0.1

Type RM Length L Ch R = 1 ,4771    ,371.8,372.2,366.2
XS GIS Cut Line= 3
2038064.20260455239865.4082455322037878.95512866240088.045120227
2037629.12596392240392.258865038
#Sta/Elev= 30
       0 1629.21    16.9 1623.05    32.3 1615.16      51 1607.06    72.4 1595.56
    97.6  1580.9   106.5 1574.97   123.6 1562.14   136.4 1550.95   148.8 1538.46
   158.7 1529.69   165.1 1521.93   170.5 1512.53   174.4 1507.12   179.1 1503.44
   183.3 1501.27   189.4 1499.09   204.7 1498.72   216.4 1499.23   225.3 1502.16
   232.7 1503.29   247.3 1502.69   268.7 1503.92   357.9 1504.52   402.8  1506.5
   485.3 1512.33   523.5 1517.97     559 1521.78   633.6 1524.86   683.3  1528.5
#Mann= 3 ,-1 , 0
       0      .1       0   183.3    .045       0   225.3     .04       0
#XS Ineff= 2 , 0
                          340.34         1514.97
Permanent Ineff=
       F       F
Bank Sta=183.3,225.3
XS Rating Curve= 0 ,0
Exp/Cntr(USF)=0,0
Exp/Cntr=0.3,0.1

Type RM Length L Ch R = 1 ,4398    ,390.6,397.1,407.9
XS GIS Cut Line= 3
2037718.02775717239694.1987893742037530.80884025239951.624800137
2037287.14892632240247.595882031
#Sta/Elev= 30
       0 1598.41    13.5 1589.87    20.8 1584.47      33 1577.14    53.3 1562.66
    74.8 1549.06    97.9  1535.6   125.8 1521.45   136.2 1513.84   142.5 1510.53
   152.9 1503.42   156.3 1502.18   166.9 1499.75   199.3  1498.4   203.4 1498.53
   210.3 1501.32   217.4  1502.5   268.3 1501.58   325.4 1502.47   369.6 1505.59
   392.4 1506.11   446.6 1509.46   469.9 1508.44   516.3 1510.96   579.4 1517.82
   628.4 1525.35   678.1 1536.35   682.4 1537.82   691.3 1542.79   701.7 1542.66
#Mann= 3 ,-1 , 0
       0      .1       0   156.3    .045       0   210.3     .04       0
#XS Ineff= 2 , 0
                             310            1508
Permanent Ineff=
       F       F
Bank Sta=156.3,210.3
XS Rating Curve= 0 ,0
Exp/Cntr(USF)=0,0
Exp/Cntr=0.3,0.1

Type RM Length L Ch R = 1 ,4001    ,437.1,510.8,492.7
XS GIS Cut Line= 4
2037420.68006559239504.2266530892037215.56522279 239709.34149589
2037062.76154795239877.2878772432036973.28191854239979.156993802
#Sta/Elev= 30
       0 1534.06     8.9  1530.6    36.1 1522.05    55.9 1516.79    74.4 1513.07
   134.7 1506.18   153.3 1504.69   168.9 1500.94   171.9 1501.01   180.5 1503.45
   184.6  1503.3   206.1 1499.54   212.4  1497.3   218.3 1495.77   232.2 1495.34
   245.5 1495.66   250.7 1497.28   258.8 1499.27   374.2 1500.51     415 1503.32
   425.5 1504.77   442.9 1504.43   521.8 1508.13   545.4 1509.32   579.7 1512.47
   601.5 1521.53   614.8 1521.79     619 1522.69   636.5 1536.69   652.7 1546.42
#Mann= 6 ,-1 , 0
       0      .1       0   212.4    .045       0   250.7     .04       0
   521.8     .05       0   601.5    .016       0     619      .1       0
#XS Ineff= 2 , 0
          181.41 1504.55  359.66         1506.51
Permanent Ineff=
       F       F
#Block Obstruct= 1 ,-1
  469.69  512.57 1527.69
Bank Sta=212.4,250.7
XS Rating Curve= 0 ,0
Exp/Cntr(USF)=0,0
Exp/Cntr=0.3,0.1

Type RM Length L Ch R = 1 ,3490    ,315,345,352.5
XS GIS Cut Line= 3
2037347.16676285239198.7415270052036866.77365668239442.939872709
2036618.11662027239571.680527567
#Sta/Elev= 30
       0 1534.07    20.8 1524.06    34.5 1519.09      75 1510.55   124.2 1504.71
   222.2 1500.11     238 1500.98   274.6 1498.99   417.3 1496.33   442.8 1497.38
   457.8 1496.48     535 1497.43   569.7 1495.09   597.8 1491.56   611.1 1491.99
   617.3 1495.71   620.9 1497.05   643.9 1497.33   682.8 1496.84   696.3 1494.86
     705 1496.71   712.4 1500.86   727.1 1512.88   730.8 1514.29   749.9 1516.82
     753 1519.67   766.9  1536.8   789.9 1553.07   798.6 1557.34   818.9 1562.66
#Mann= 7 ,-1 , 0
       0      .1       0   134.8     .03       0   285.2      .1       0
   569.7    .045       0   617.3      .1       0   706.8    .016       0
   733.5      .1       0
#XS Ineff= 2 , 0
          300.17 1506.28
Permanent Ineff=
       F       F
Bank Sta=569.7,617.3
XS Rating Curve= 0 ,0
Exp/Cntr(USF)=0,0
Exp/Cntr=0.3,0.1

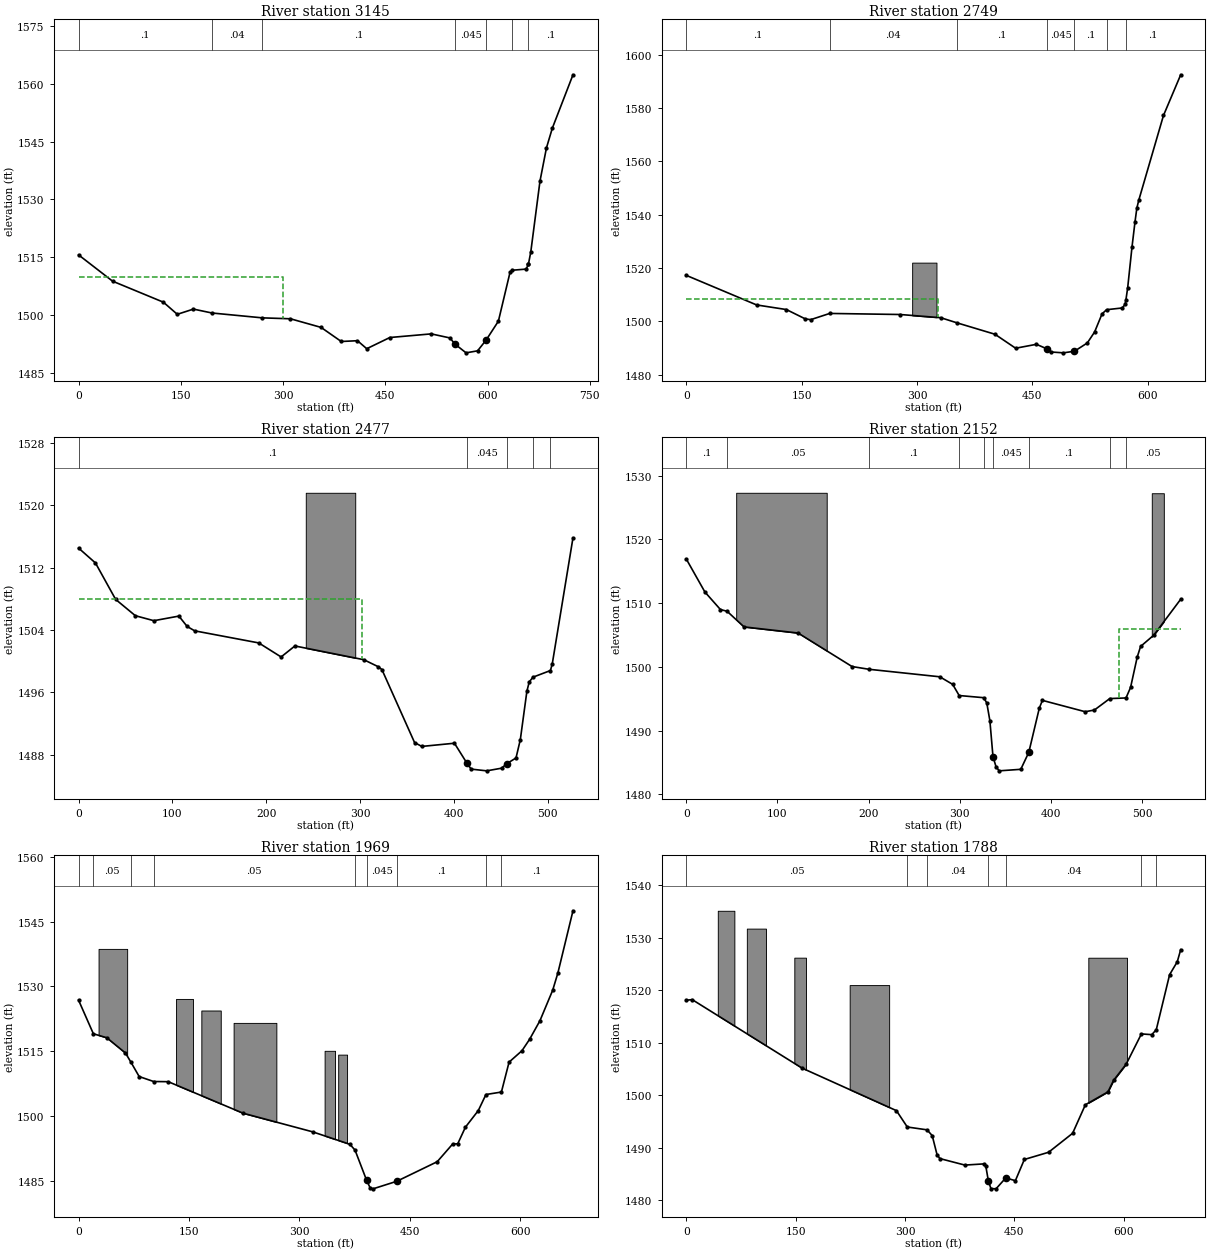
Type RM Length L Ch R = 1 ,3145    ,272.7,396.5,418.1
Node Name=A
XS GIS Cut Line= 2
2037233.46114867239014.1536058612036531.39021023239195.866084047
#Sta/Elev= 30
       0 1515.65    49.9 1508.84   124.4  1503.4   144.8 1500.26   168.5 1501.61
   195.6  1500.6   269.6 1499.34   310.8  1499.1   355.7 1496.87   385.3 1493.22
   409.1 1493.42   422.7 1491.35   456.6 1494.25   517.3 1495.19   544.7 1494.14
   552.3 1492.51   568.4 1490.28   585.3  1490.8     598 1493.64   615.8 1498.48
   632.8 1511.09   635.7 1511.67   656.5 1511.97   659.9 1513.25   659.9 1513.29
   663.3 1516.39   676.8 1534.76   686.3 1543.36   694.9 1548.46   725.2  1562.3
#Mann= 7 ,-1 , 0
       0      .1       0   195.6     .04       0   269.6      .1       0
   552.3    .045       0     598      .1       0   635.7    .016       0
   659.9      .1       0
#XS Ineff= 2 , 0
             300    1510
Permanent Ineff=
       F       F
Bank Sta=552.3,598
XS Rating Curve= 0 ,0
Exp/Cntr(USF)=0,0
Exp/Cntr=0.3,0.1

Type RM Length L Ch R = 1 ,2749    ,272.2,271.5,272.2
XS GIS Cut Line= 3
2037237.59097772238994.8810702962036904.45143438238865.479760073
2036660.79152045238716.805914285
#Sta/Elev= 30
       0 1517.26    91.4 1506.16   130.1 1504.43   154.8 1500.91   161.8 1500.64
   186.5 1502.97     278 1502.57   330.8 1501.37   351.6 1499.47   401.3 1495.16
   428.2 1489.91   455.2 1491.38   468.9 1489.68   474.4 1488.49   490.4 1488.18
   504.7 1488.79   521.4 1491.89   530.9 1496.03   540.5 1502.78   546.4 1504.37
   566.7 1505.02   570.5 1506.34   571.5  1507.9   573.9 1512.66   579.5 1527.95
   583.4 1537.37   585.8 1542.52   588.2 1545.38   620.4 1577.27   642.8 1592.55
#Mann= 7 ,-1 , 0
       0      .1       0   186.5     .04       0   351.6      .1       0
   468.9    .045       0   504.7      .1       0   546.4    .016       0
   571.5      .1       0
#XS Ineff= 2 , 0
          327.32 1508.49
Permanent Ineff=
       F       F
#Block Obstruct= 1 ,-1
  293.65  325.25 1522.04
Bank Sta=468.9,504.7
XS Rating Curve= 0 ,0
Exp/Cntr(USF)=0,0
Exp/Cntr=0.3,0.1

Type RM Length L Ch R = 1 ,2477    ,334.8,325.6,300.1
XS GIS Cut Line= 2
2037328.44721682238811.7919824272036881.04906977238533.716826416
#Sta/Elev= 30
       0  1514.5      18 1512.59    39.5 1507.92    60.5 1505.83    80.2 1505.19
   106.9 1505.78   115.7 1504.45   123.7 1503.89     192 1502.34   215.8 1500.54
   230.5 1501.95   303.9 1500.19   319.3 1499.29   323.2 1498.93     358 1489.57
   365.7 1489.07   400.5 1489.48   413.5 1486.98   418.3 1486.16   434.9 1485.94
   450.7 1486.28   456.4 1486.87   466.1 1487.59   470.7 1489.94   477.7 1496.15
   480.2 1497.34   484.2 1497.95   502.8  1498.8   504.8  1499.7   526.8 1515.81
#Mann= 5 ,-1 , 0
       0      .1       0   413.5    .045       0   456.4      .1       0
   484.2    .016       0   502.8      .1       0
#XS Ineff= 2 , 0
          301.52    1508
Permanent Ineff=
       F       F
#Block Obstruct= 1 ,-1
  242.09  294.79 1521.59
Bank Sta=413.5,456.4
XS Rating Curve= 0 ,0
Exp/Cntr(USF)=0,0
Exp/Cntr=0.3,0.1

Type RM Length L Ch R = 1 ,2152    ,176.2,182.9,180.5
XS GIS Cut Line= 5
2037487.30797426238494.8964333492037198.63292369238343.744690131
2037113.14546236238321.4436132632037014.58020904238273.537596287
2036998.06089284238265.277938187
#Sta/Elev= 30
       0 1516.92    20.4 1511.75    37.4    1509    44.8 1508.72    63.3 1506.27
   122.6 1505.31   181.8 1500.05   200.3 1499.62   278.1 1498.44   292.2 1497.25
   299.3  1495.5   326.2 1495.16   329.6 1494.34     333 1491.55   336.4 1485.91
   339.8  1484.3   343.2 1483.68   366.9 1483.92   375.7 1486.59   387.2 1493.51
   390.6 1494.74   437.5 1492.96   447.6 1493.22   464.5 1495.02   482.3 1495.12
   487.3 1496.76   494.6 1501.53   498.3  1503.2   512.9 1504.99   542.3 1510.61
#Mann= 9 ,-1 , 0
       0      .1       0    44.8     .05       0   200.3      .1       0
   299.3    .016       0   326.2      .1       0   336.4    .045       0
   375.7      .1       0   464.5    .016       0   482.3     .05       0
#XS Ineff= 2 , 0
                             475            1506
Permanent Ineff=
       F       F
#Block Obstruct= 2 ,-1
   54.72  154.02 1527.32  510.58  523.79 1527.25
Bank Sta=336.4,375.7
XS Rating Curve= 0 ,0
Exp/Cntr(USF)=0,0
Exp/Cntr=0.3,0.1

Type RM Length L Ch R = 1 ,1969    ,173.6,180.6,170.1
XS GIS Cut Line= 3
2037583.94597402238332.5941516972037254.38561586238176.486613619
2036965.71056529238072.414921568
#Sta/Elev= 30
       0 1526.79    20.1 1519.01    38.3 1518.09    63.7 1514.54      71 1512.46
    82.3  1509.1     102 1507.95   121.8 1507.91   223.4 1500.61   317.8  1496.3
   368.5 1493.41   375.5 1492.06   391.2 1485.07   396.2 1483.26   399.9 1483.09
   432.2 1484.84   487.1 1489.37     508 1493.46     515 1493.53   525.4 1497.37
   542.9 1501.22   553.3 1504.94   574.3 1505.51   584.7 1512.44   602.2 1515.08
   612.6 1517.73   626.6 1522.02     644 1529.12     651 1533.09   671.5  1547.5
#Mann= 9 ,-1 , 0
       0      .1       0    20.1     .05       0      71    .016       0
     102     .05       0   375.5      .1       0   391.2    .045       0
   432.2      .1       0   553.3    .016       0   574.3      .1       0
#Block Obstruct= 6 ,-1
   27.15   65.99 1538.67   132.4  155.35 1527.08  166.74  193.11  1524.4
  210.58  268.64 1521.53  334.17  348.35 1515.06  352.59  364.66 1514.18
Bank Sta=391.2,432.2
XS Rating Curve= 0 ,0
Exp/Cntr(USF)=0,0
Exp/Cntr=0.3,0.1

Type RM Length L Ch R = 1 ,1788    ,212.3,229.2,209.5
XS GIS Cut Line= 2
2037668.46980857238151.4323173852037033.16443976 237913.82948606
#Sta/Elev= 30
       0 1518.09     8.1 1518.21   158.7 1505.16   288.3 1497.04   303.2 1493.92
   330.3 1493.38   337.4 1492.28     344 1488.65   347.9  1487.9   382.2 1486.66
   408.6 1486.89   410.9 1486.49   414.4 1483.65   417.9 1482.19   424.9 1482.13
   438.3 1484.21   451.5 1483.69   463.8 1487.73     497  1489.1     530 1492.72
   547.5 1498.16   578.5 1500.62   586.2 1502.81   603.6 1505.93   624.4 1511.67
   638.6 1511.53   644.8 1512.47   663.1 1522.97   673.6 1525.43   678.3 1527.73
#Mann= 7 ,-1 , 0
       0     .05       0   303.2    .016       0   330.3     .04       0
   414.4    .045       0   438.3     .04       0   624.4    .016       0
   644.8      .1       0
#Block Obstruct= 5 ,-1
   43.21   65.95 1535.15   83.06  109.29 1531.75   148.2  164.17 1526.21
  224.14  278.31 1520.98  551.56   604.6  1526.2
Bank Sta=414.4,438.3
XS Rating Curve= 0 ,0
Exp/Cntr(USF)=0,0
Exp/Cntr=0.3,0.1