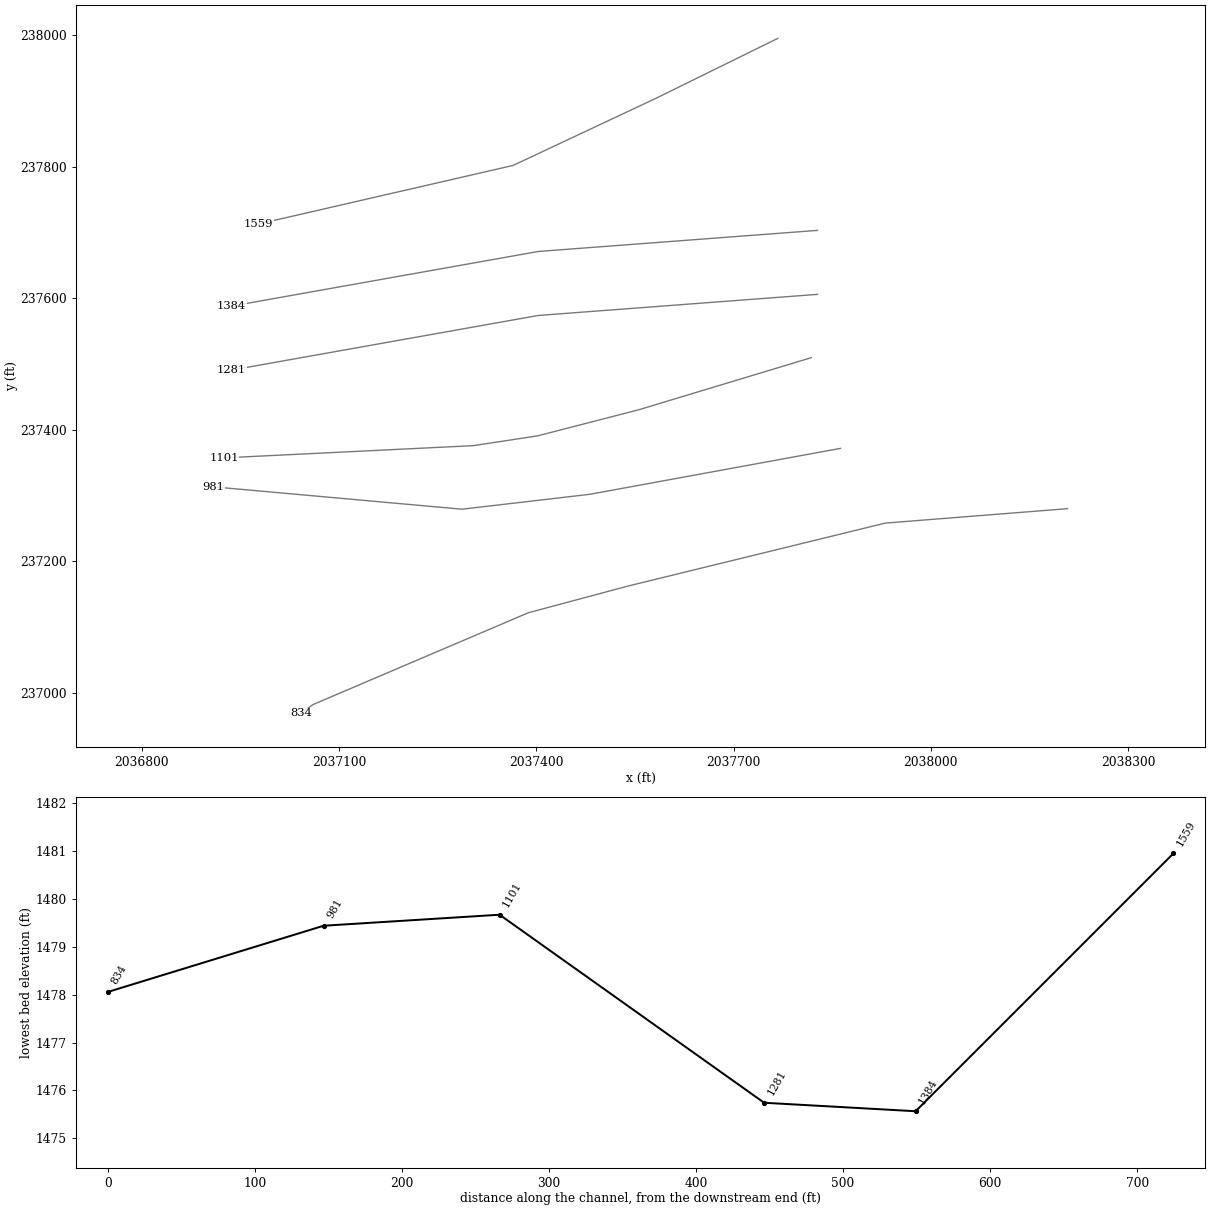
HEC-RAS study HNGRDCK_AE.prj: HNGRDCK_AE

--- HNGRDCK_AE.g01 (geometry) --- (continued)

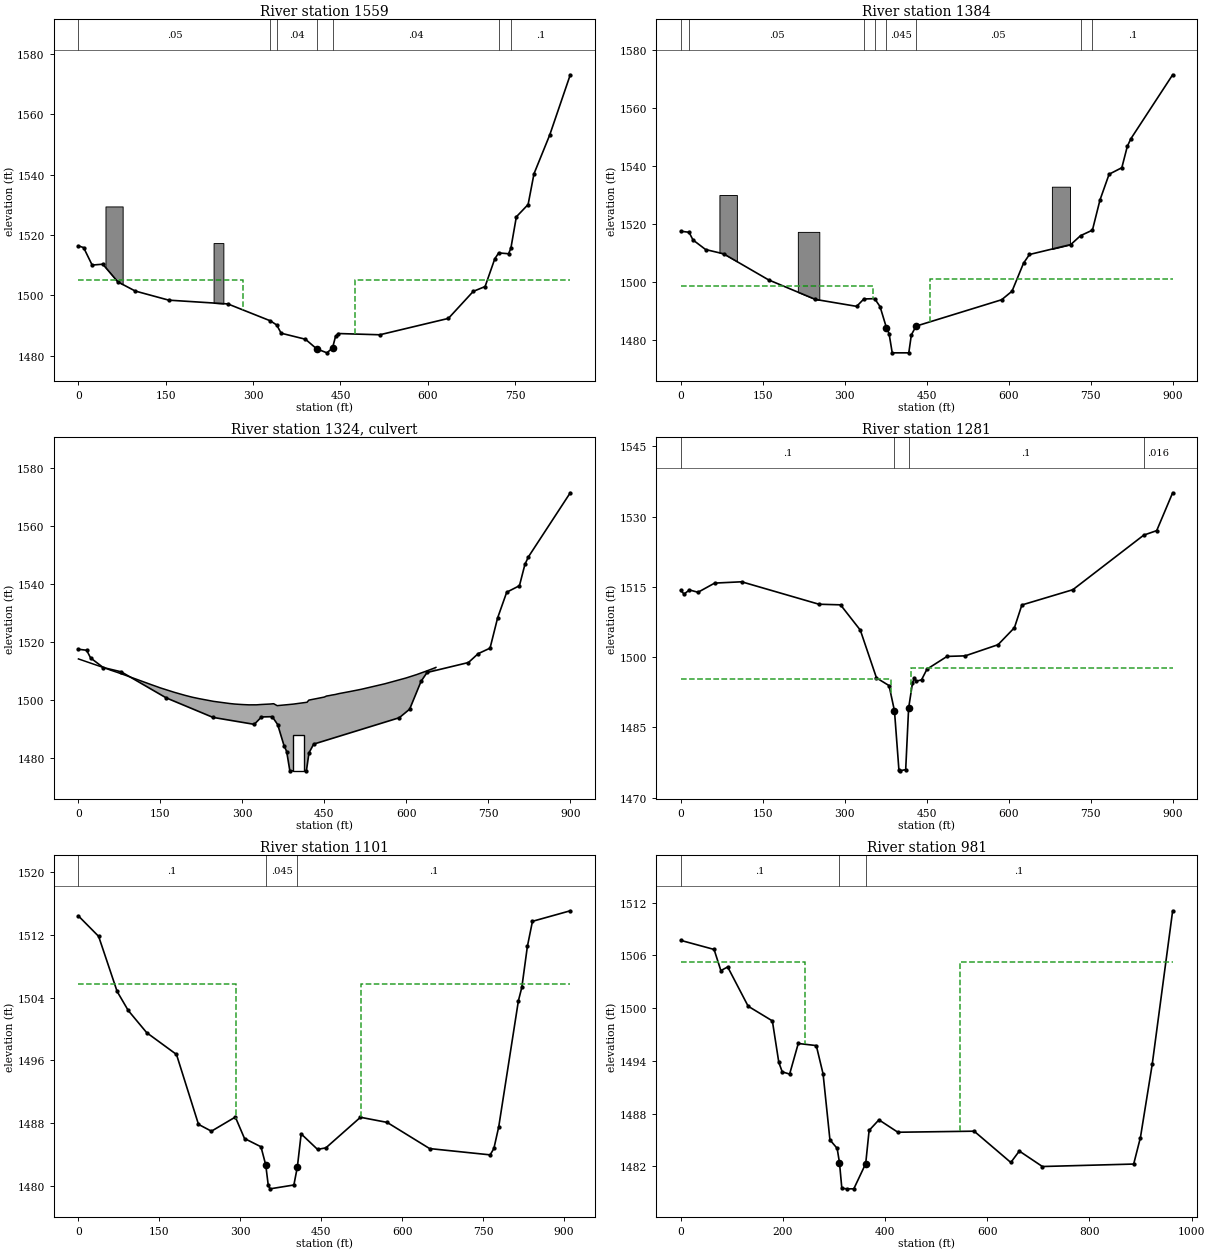
Type RM Length L Ch R = 1 ,1559    ,177.7,175.3,144.5
XS GIS Cut Line= 4
 2037767.3103839237995.6001012832037581.98227043237904.473200942
2037364.65205148237802.3241017192036976.86110372237713.119794246
#Sta/Elev= 30
       0 1516.42     8.9 1515.85    23.5 1510.06    41.8 1510.34    67.6 1504.49
    97.6 1501.44   155.1 1498.42   256.6 1497.17   329.6 1491.56   340.5 1490.18
   348.1 1487.46   389.8 1485.46     409 1482.29   426.7 1480.95   436.3 1482.55
   441.5  1486.4   446.5 1487.35   517.6 1486.94   635.3 1492.37     678 1501.33
   698.3 1502.93     715 1512.15   721.7 1514.09   738.6 1513.81   742.6 1515.63
     752 1526.06   772.2 1530.14   782.3 1540.34   809.3 1553.19   844.6 1573.16
#Mann= 7 ,-1 , 0
       0     .05       0   329.6    .016       0   340.5     .04       0
     409    .045       0   436.3     .04       0   721.7    .016       0
   742.6      .1       0
#XS Ineff= 2 , 0
          282.25    1505     475            1505
Permanent Ineff=
       F       F
#Block Obstruct= 2 ,-1
   46.41   75.91  1529.5  232.05  248.88 1517.35
Bank Sta=409,436.3
XS Rating Curve= 0 ,0
Exp/Cntr(USF)=0,0
Exp/Cntr=0.5,0.3

Type RM Length L Ch R = 1 ,1384    ,103.2,103,101.8
BEGIN DESCRIPTION:
Channel burned based on survey: 54089HUC022CU
END DESCRIPTION:
XS GIS Cut Line= 3
2037827.50515145237703.5239236992037402.62561959237671.421914626
2036936.20231128237588.334361729
#Sta/Elev= 30
       0 1517.46      15 1517.11    22.3 1514.45    45.4 1511.15    78.3 1509.68
   160.5 1500.71   246.1 1493.98   321.7 1491.58   334.9 1494.13   354.6 1494.23
   364.5 1491.51   376.1 1484.28     381 1482.21   386.81475.567   417.11475.567
   421.8 1481.75   430.4 1484.77     587 1493.86     606 1496.81     627 1506.44
   637.9 1509.45   713.5 1512.88   731.4 1515.94   753.1 1517.84   766.9 1528.22
   783.6 1537.11   806.9 1539.35   816.9 1546.69   823.3 1549.29   899.9 1571.37
#Mann= 8 ,-1 , 0
       0    .016       0      15     .05       0   334.9    .016       0
   354.6      .1       0   376.1    .045       0   430.4     .05       0
   731.4    .016       0   753.1      .1       0
#XS Ineff= 2 ,-1
       0     351 1498.48     455899.8566 1500.99
Permanent Ineff=
       F       F
#Block Obstruct= 3 ,-1
   70.61  102.54 1529.94   214.1  253.37 1517.24  678.95  712.01 1532.81
Bank Sta=376.1,430.4
XS Rating Curve= 0 ,0
Exp/Cntr(USF)=0,0
Exp/Cntr=0.5,0.3

Type RM Length L Ch R = 2 ,1324    ,,,
BEGIN DESCRIPTION:
State Route 3
Survey ID: 54089HUC020
END DESCRIPTION:
Bridge Culvert--1,0,-1,-1, 0
Deck Dist Width WeirC Skew NumUp NumDn MinLoCord MaxHiCord MaxSubmerge Is_Ogee
53,27,2.6,0, 179, 179, , , 0.98, 0, 0,0,,
       0   3.257   6.514    9.77  13.027  16.284  19.541  22.797  26.054  29.311
  32.568  35.825  39.081  42.338  45.595  48.852  52.108  55.365  58.622  61.879
  65.135  68.392  71.649  74.906  78.163  81.419  84.676  87.933   91.19  94.446
  97.703  100.96 104.217 107.474  110.73 113.987 117.244 120.501 123.757 127.014
 130.271 133.528 136.785 140.041 143.287 146.533 149.778 153.024 156.269 159.515
 162.761 166.006 169.252 172.498 175.743 178.989 182.234  185.48 188.726 191.971
 195.217 198.463 201.708 204.954 208.199 211.445 214.691 217.936 221.182 224.428
 227.673 230.919 234.165  237.41 240.656 243.901 247.147 250.393 253.638 256.884
  260.13 263.375 266.621 269.866 273.112 276.358 279.603 282.849 286.095  289.34
 292.586 295.831 299.077 302.323 305.568 308.814  312.06 315.305 318.551 321.768
 324.986 328.203 331.421 334.638 337.856 341.073 344.291 347.508 350.726 353.943
  357.16 363.595     393 418.292  421.51     450 453.709 456.939 460.168 463.398
 466.628 469.858 473.087 476.317 479.547 482.777 486.006 489.236 492.466 495.696
 498.925 502.155 505.385 508.615 511.844 515.074 518.304 521.534 524.763 527.993
 531.223 534.453 537.682 540.912 544.142 547.372 550.601 553.831 557.061 560.291
  563.52  566.75  569.98  573.21  576.44 579.669 582.899 586.129 589.359 592.588
 595.818 599.048 602.278 605.507 608.737 611.967 615.196 618.426 621.656 624.886
 628.115 631.345 634.575 637.805 641.034 644.264 647.494 650.764 654.033
1514.1231513.9151513.7151513.5161513.3081513.0981512.8851512.6651512.4521512.246
 1512.031511.8231511.6061511.3811511.1461510.9531510.7491510.5041510.271 1510.07
1509.8741509.6861509.4511509.2221509.0131508.794 1508.58 1508.361508.161 1507.93
1507.6951507.4751507.257 1507.031506.7831506.5591506.3381506.1151505.9041505.698
 1505.481505.2451505.0391504.8351504.5971504.3621504.1521503.9541503.7491503.563
1503.3861503.2011502.9981502.7931502.6081502.4281502.249 1502.091501.9211501.744
1501.5661501.4031501.2621501.1011500.9441500.8091500.6771500.5451500.4281500.311
1500.172 1500.051499.9521499.8461499.7271499.608 1499.511499.4241499.3431499.263
1499.1741499.0751498.9911498.9211498.8471498.7711498.6941498.6271498.578 1498.53
1498.4771498.4361498.4141498.3811498.3471498.3371498.3051498.2951498.3021498.313
1498.3061498.3561498.4091498.4291498.4531498.4861498.5391498.5551498.586 1498.64
1498.6981498.0281498.557  1499.21499.9321500.9941501.3321501.4311501.5391501.671
1501.7541501.8731502.0311502.1681502.2771502.3811502.5011502.6271502.7351502.854
1502.979 1503.111503.2371503.3571503.4521503.5581503.7021503.8421503.9761504.121
1504.2511504.3771504.5111504.6631504.795 1504.941505.0881505.2411505.4011505.549
1505.7131505.8991506.032 1506.181506.357 1506.531506.6921506.867 1507.041507.197
1507.3671507.5441507.7341507.9341508.1341508.324 1508.511508.7091508.9251509.144
1509.3691509.5811509.7951510.026 1510.271510.4861510.7081510.9581511.214
                                                                                
                                                                                
                                                                                
                                                                                
                                                                                
                                                                                
                                                                                
                                                                                
                                                                                
                                                                                
                                                                                
                                                                                
                                                                                
                                                                                
                                                                                
                                                                                
                                                                                
                                                                        
       0   3.257   6.514    9.77  13.027  16.284  19.541  22.797  26.054  29.311
  32.568  35.825  39.081  42.338  45.595  48.852  52.108  55.365  58.622  61.879
  65.135  68.392  71.649  74.906  78.163  81.419  84.676  87.933   91.19  94.446
  97.703  100.96 104.217 107.474  110.73 113.987 117.244 120.501 123.757 127.014
 130.271 133.528 136.785 140.041 143.287 146.533 149.778 153.024 156.269 159.515
 162.761 166.006 169.252 172.498 175.743 178.989 182.234  185.48 188.726 191.971
 195.217 198.463 201.708 204.954 208.199 211.445 214.691 217.936 221.182 224.428
 227.673 230.919 234.165  237.41 240.656 243.901 247.147 250.393 253.638 256.884
  260.13 263.375 266.621 269.866 273.112 276.358 279.603 282.849 286.095  289.34
 292.586 295.831 299.077 302.323 305.568 308.814  312.06 315.305 318.551 321.768
 324.986 328.203 331.421 334.638 337.856 341.073 344.291 347.508 350.726 353.943
  357.16 363.595     393 418.292  421.51     450 453.709 456.939 460.168 463.398
 466.628 469.858 473.087 476.317 479.547 482.777 486.006 489.236 492.466 495.696
 498.925 502.155 505.385 508.615 511.844 515.074 518.304 521.534 524.763 527.993
 531.223 534.453 537.682 540.912 544.142 547.372 550.601 553.831 557.061 560.291
  563.52  566.75  569.98  573.21  576.44 579.669 582.899 586.129 589.359 592.588
 595.818 599.048 602.278 605.507 608.737 611.967 615.196 618.426 621.656 624.886
 628.115 631.345 634.575 637.805 641.034 644.264 647.494 650.764 654.033
1514.1231513.9151513.7151513.5161513.3081513.0981512.8851512.6651512.4521512.246
 1512.031511.8231511.6061511.3811511.1461510.9531510.7491510.5041510.271 1510.07
1509.8741509.6861509.4511509.2221509.0131508.794 1508.58 1508.361508.161 1507.93
1507.6951507.4751507.257 1507.031506.7831506.5591506.3381506.1151505.9041505.698
 1505.481505.2451505.0391504.8351504.5971504.3621504.1521503.9541503.7491503.563
1503.3861503.2011502.9981502.7931502.6081502.4281502.249 1502.091501.9211501.744
1501.5661501.4031501.2621501.1011500.9441500.8091500.6771500.5451500.4281500.311
1500.172 1500.051499.9521499.8461499.7271499.608 1499.511499.4241499.3431499.263
1499.1741499.0751498.9911498.9211498.8471498.7711498.6941498.6271498.578 1498.53
1498.4771498.4361498.4141498.3811498.3471498.3371498.3051498.2951498.3021498.313
1498.3061498.3561498.4091498.4291498.4531498.4861498.5391498.5551498.586 1498.64
1498.6981498.0281498.557  1499.21499.9321500.9941501.3321501.4311501.5391501.671
1501.7541501.8731502.0311502.1681502.2771502.3811502.5011502.6271502.7351502.854
1502.979 1503.111503.2371503.3571503.4521503.5581503.7021503.8421503.9761504.121
1504.2511504.3771504.5111504.6631504.795 1504.941505.0881505.2411505.4011505.549
1505.7131505.8991506.032 1506.181506.357 1506.531506.6921506.867 1507.041507.197
1507.3671507.5441507.7341507.9341508.1341508.324 1508.511508.7091508.9251509.144
1509.3691509.5811509.7951510.026 1510.271510.4861510.7081510.9581511.214
                                                                                
                                                                                
                                                                                
                                                                                
                                                                                
                                                                                
                                                                                
                                                                                
                                                                                
                                                                                
                                                                                
                                                                                
                                                                                
                                                                                
                                                                                
                                                                                
                                                                                
                                                                        
BR Coef=-1 , 1 , 0 ,, 0 ,,,0.8,0,1.2,0,
WSPro=,,,, 1 ,,,, 0 ,,,, 0 ,,,,-1 ,-1 ,-1 , 0 , 0 , 0 , 0 , 0
Culvert=2,12.3,20,48,0.012,0.2,1,10,2,1475.567,403,1475.744,405,Culvert #1  , 0 ,38
     403     405
BC Culvert Barrel=1,Barrel1,0
Culvert Bottom n=0.012
BC Design=,, 0 ,, 0 ,,,,,,
BC Use User HTab Curves=0
BC User HTab FreeFlow(D)= 0

Type RM Length L Ch R = 1 ,1281    ,178.4,179.9,188.9
BEGIN DESCRIPTION:
Channel burned based on survey: 54089HUC018CD
END DESCRIPTION:
XS GIS Cut Line= 3
2037827.57401282237606.2108641642037402.69448096 237574.10885509
2036936.27117265237491.021302193
#Sta/Elev= 30
       0 1514.25     5.9 1513.48    15.8 1514.36    31.4 1513.86    61.9 1515.82
   111.2  1516.1   252.7 1511.31   292.2 1511.18   328.4 1505.78     358 1495.58
     381 1493.94   390.9 1488.55  399.03 1475.96   400.81475.744  411.44 1476.01
   416.8 1489.13   423.8 1494.42   427.1  1495.6   430.4 1494.87   440.4 1495.17
   450.4 1497.45   487.1 1500.17   520.4 1500.29   580.4 1502.67   610.4  1506.3
     624 1511.15   717.3 1514.41     847 1526.06   870.7 1527.02   899.9  1535.1
#Mann= 4 ,-1 , 0
       0      .1       0   390.9    .045       0   416.8      .1       0
     847    .016       0
#XS Ineff= 2 ,-1
       0     385  1495.4     421 899.857  1497.8
Permanent Ineff=
       F       F
Bank Sta=390.9,416.8
XS Rating Curve= 0 ,0
Exp/Cntr(USF)=0,0
Exp/Cntr=0.5,0.3

Type RM Length L Ch R = 1 ,1101    ,118,119.6,97.6
XS GIS Cut Line= 5
2037818.10728114237509.9322050022037555.45015358237430.639487248
2037401.82051293237390.9931283712037303.94356445237376.125743793
2036924.82525769237357.541513069
#Sta/Elev= 30
       0 1514.37    37.4 1511.78    71.7 1504.77    92.3 1502.35   126.5 1499.53
   181.7 1496.76   222.5 1487.87   246.5    1487   290.8  1488.8   307.8 1486.07
   338.3 1485.02   347.11482.724   351.8 1480.13   355.2 1479.67   399.3 1480.16
   405.8 1482.47   412.8 1486.66   443.1 1484.69   458.6 1484.88   522.7 1488.77
   572.1 1488.12   650.9 1484.79   763.1 1483.99     770  1484.8     779 1487.56
   815.5  1503.6   821.8 1505.29   832.1  1510.5   841.5 1513.69   911.6 1515.03
#Mann= 3 ,-1 , 0
       0      .1       0   347.1    .045       0   405.8      .1       0
#XS Ineff= 2 , 0
          292.39  1505.7  523.38          1505.7
Permanent Ineff=
       F       F
Bank Sta=347.1,405.8
XS Rating Curve= 0 ,0
Exp/Cntr(USF)=0,0
Exp/Cntr=0.3,0.1

Type RM Length L Ch R = 1 ,981     ,146.5,146.8,161.7
XS GIS Cut Line= 4
2037862.67460191237372.0026992872037481.22719997237302.133620715
2037286.72679205237279.4733790162036909.05609707237313.463741564
#Sta/Elev= 30
       0 1507.71    65.1 1506.68    78.4 1504.27    91.7 1504.69   131.8 1500.22
   179.2 1498.55   191.8 1493.83   198.5 1492.75     213  1492.5   229.9 1495.98
   265.2 1495.74   278.5 1492.51   291.9 1485.01     306 1484.05   310.6 1482.41
   315.2 1479.49   325.8 1479.44   338.6 1479.44   361.9 1482.31   368.6 1486.09
   387.8 1487.29   424.9 1485.88   574.2    1486     646 1482.44   662.6 1483.74
   707.8 1481.98   886.5 1482.26   899.7 1485.28   922.8 1493.61   962.8 1511.08
#Mann= 3 ,-1 , 0
       0      .1       0   310.6    .045       0   361.9      .1       0
#XS Ineff= 2 , 0
          243.38 1505.25  547.04         1505.25
Permanent Ineff=
       F       F
Bank Sta=310.6,361.9
XS Rating Curve= 0 ,0
Exp/Cntr(USF)=0,0
Exp/Cntr=0.5,0.3

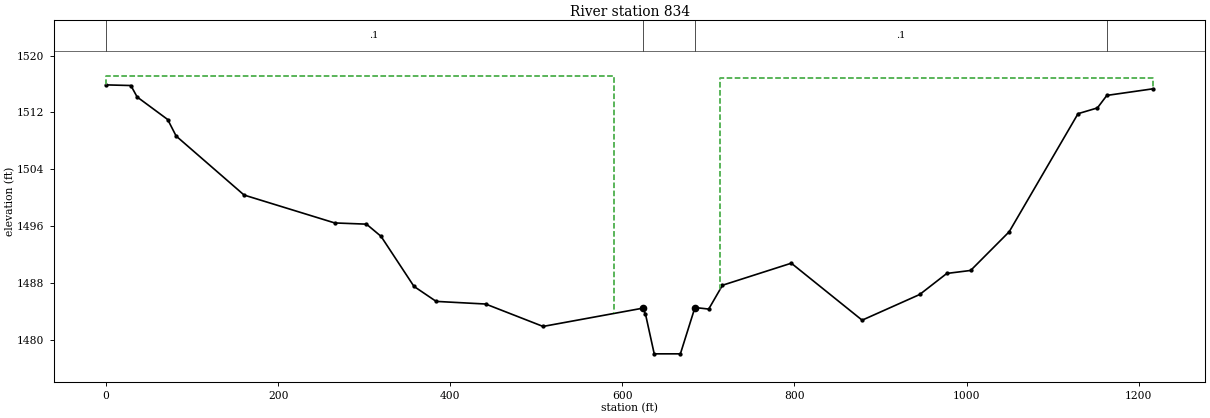
Type RM Length L Ch R = 1 ,834     ,232.4,240.9,233.4
BEGIN DESCRIPTION:
Channel burned based on survey: 54089HUC012CU
END DESCRIPTION:
XS GIS Cut Line= 6
 2038207.9552748237280.2866635872037930.71182841237258.356896071
2037538.79947717237162.4445996152037387.51879179237121.911053421
2037060.02286609236982.2790999692037041.95010588236968.954421952
#Sta/Elev= 30
       0 1515.87    28.8 1515.78    36.1 1514.17    71.6    1511    81.4 1508.68
   160.4 1500.38   265.7 1496.46   302.6 1496.29   319.5 1494.58   357.8 1487.54
   383.6 1485.43   441.1 1485.06   507.8 1481.91   623.4 1484.47   626.8 1483.67
     6371478.057   667.41478.057   684.3 1484.57   700.3 1484.35   716.3  1487.7
   796.3  1490.8   878.6 1482.79   945.5  1486.4     977 1489.36  1004.7 1489.78
  1049.5 1495.22  1129.5 1511.82    1152 1512.63    1163 1514.39  1216.7 1515.32
#Mann= 4 ,-1 , 0
       0      .1       0   623.4    .045       0   684.3      .1       0
    1163    .016       0
#XS Ineff= 2 ,-1
       0     590 1517.15     7131216.678  1516.9
Permanent Ineff=
       F       F
Bank Sta=623.4,684.3
XS Rating Curve= 0 ,0
Exp/Cntr(USF)=0,0
Exp/Cntr=0.5,0.3