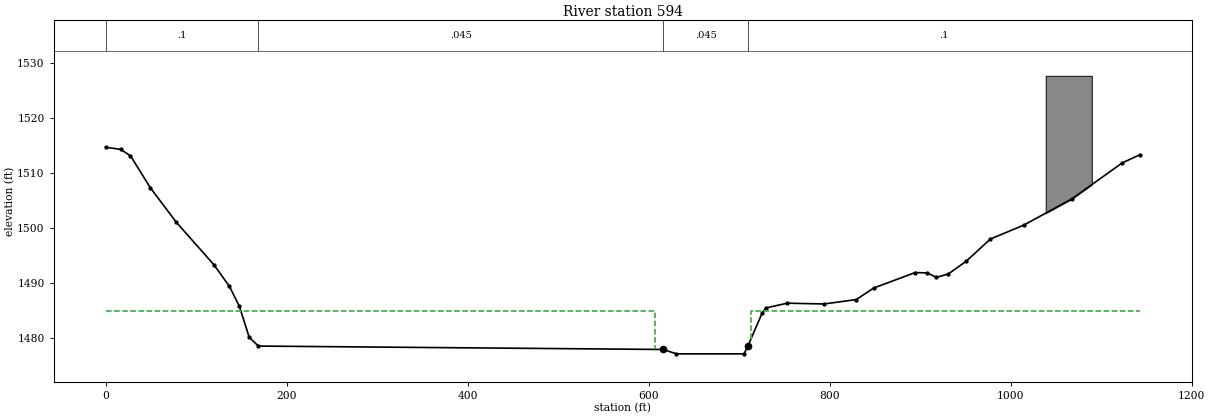
HEC-RAS study HNGRDCK_AE.prj: HNGRDCK_AE

--- HNGRDCK_AE.g01 (geometry) --- (continued)

Type RM Length L Ch R = 2 ,727     ,,,
BEGIN DESCRIPTION:
CSX
Bridge ID:  54089HUC010
END DESCRIPTION:
Bridge Culvert--1,0,-1,-1, 0
Deck Dist Width WeirC Skew NumUp NumDn MinLoCord MaxHiCord MaxSubmerge Is_Ogee
53,115,2.6,0, 60, 60, , , 0.98, 0, 0,0,,
       0  32.493  38.992   94.23 100.728 107.227 145.991 152.444 226.653 242.786
 278.252 284.697  329.81 336.254 349.144 374.922 427.076 440.182 476.225 486.054
 492.608  518.82 525.373 541.622 548.108  561.08 564.322 570.808 580.537 593.509
 609.724     610     673 677.901 697.433 713.709 729.986 772.305 791.869 824.579
 837.663 844.205 863.831 873.644 880.186 916.167 961.961  984.87 1040.511047.056
1073.2391099.4221105.9681112.5141138.6981145.2441148.5161164.8811194.3381227.067
 1516.731517.0311516.9231517.1141516.9691517.0931517.0311517.1571516.9771517.135
1517.0151517.1431517.1761516.9871517.1831517.0471517.1761516.8281517.0161516.813
1517.0521516.7451517.024 1516.621516.8911516.7141516.8531516.6571516.9261516.557
1516.7091516.9691516.9681516.8291517.032 1516.651516.8821516.8091517.0341516.957
1517.1111516.9181516.7641517.1071516.9121516.9931516.8011516.9311516.8691516.728
1516.8891516.7661516.8891516.7781516.8741516.7391516.8691516.759 1516.921516.825
                                                                                
                                                                                
                                                                                
                                                                                
                                                                                
                                                                                
       0  32.493  38.992   94.23 100.728 107.227 145.991 152.444 226.653 242.786
 278.252 284.697  329.81 336.254 349.144 374.922 427.076 440.182 476.225 486.054
 492.608  518.82 525.373 541.622 548.108  561.08 564.322 570.808 580.537 593.509
 609.724     610     673 677.901 697.433 713.709 729.986 772.305 791.869 824.579
 837.663 844.205 863.831 873.644 880.186 916.167 961.961  984.87 1040.511047.056
1073.2391099.4221105.9681112.5141138.6981145.2441148.5161164.8811194.3381227.067
 1516.731517.0311516.9231517.1141516.9691517.0931517.0311517.1571516.9771517.135
1517.0151517.1431517.1761516.9871517.1831517.0471517.1761516.8281517.0161516.813
1517.0521516.7451517.024 1516.621516.8911516.7141516.8531516.6571516.9261516.557
1516.7091516.9691516.9681516.8291517.032 1516.651516.8821516.8091517.0341516.957
1517.1111516.9181516.7641517.1071516.9121516.9931516.8011516.9311516.8691516.728
1516.8891516.7661516.8891516.7781516.8741516.7391516.8691516.759 1516.921516.825
                                                                                
                                                                                
                                                                                
                                                                                
                                                                                
                                                                                
BR Coef=-1 , 1 , 0 ,, 0 ,,,0.8,0,1.2,0,
WSPro=,,,, 1 ,,,, 0 ,,,, 0 ,,,,-1 ,-1 ,-1 , 0 , 0 , 0 , 0 , 0
Culvert=5,19.3,16,181,0.012,0.5,1,41,1,1478.057,655,1477.167,665,Culvert #1  , 0 ,21
     655     665
BC Culvert Barrel=1,Barrel 1,0
Culvert Bottom n=0.012
BC Design=,, 0 ,, 0 ,,,,,,
BC Use User HTab Curves=0
BC User HTab FreeFlow(D)= 0

Type RM Length L Ch R = 1 ,594     ,53,53,53
BEGIN DESCRIPTION:
Channel burned based on survey: 54089HUC008CD
END DESCRIPTION:
XS GIS Cut Line= 4
2038212.28631322237201.2996093882038067.22761007237092.505582025
2037603.55782679236926.7242069972037139.88804351236854.194855422
#Sta/Elev= 30
       0 1514.75    16.5 1514.37    27.5  1513.2    49.4 1507.39    78.2 1501.09
   119.7 1493.37   136.8 1489.45   147.8 1485.82   158.7 1480.17   168.9 1478.58
  616.08 1477.96  630.741477.167   705.41477.167   709.9 1478.68   725.3 1484.55
   729.6 1485.52   753.2 1486.38   793.9 1486.24   829.5 1487.04   848.5 1489.13
   894.4 1491.95   907.9 1491.89   917.9 1491.08   931.2 1491.71   951.1 1494.05
   977.6 1498.06  1014.2 1500.56  1067.3 1505.33  1123.2  1511.9    1143 1513.41
#Mann= 4 ,-1 , 0
       0      .1       0   168.9    .045       0  616.08    .045       0
   709.9      .1       0
#XS Ineff= 2 , 0
             607    1485     713            1485
Permanent Ineff=
       F       F
#Block Obstruct= 1 ,-1
 1038.67 1089.59 1527.75
Bank Sta=616.08,709.9
XS Rating Curve= 0 ,0
Exp/Cntr(USF)=0,0
Exp/Cntr=0.5,0.3
LCMann Table=0

Chan Stop Cuts=-1
Use User Specified Reach Order=0
Composite Channel Slope=5